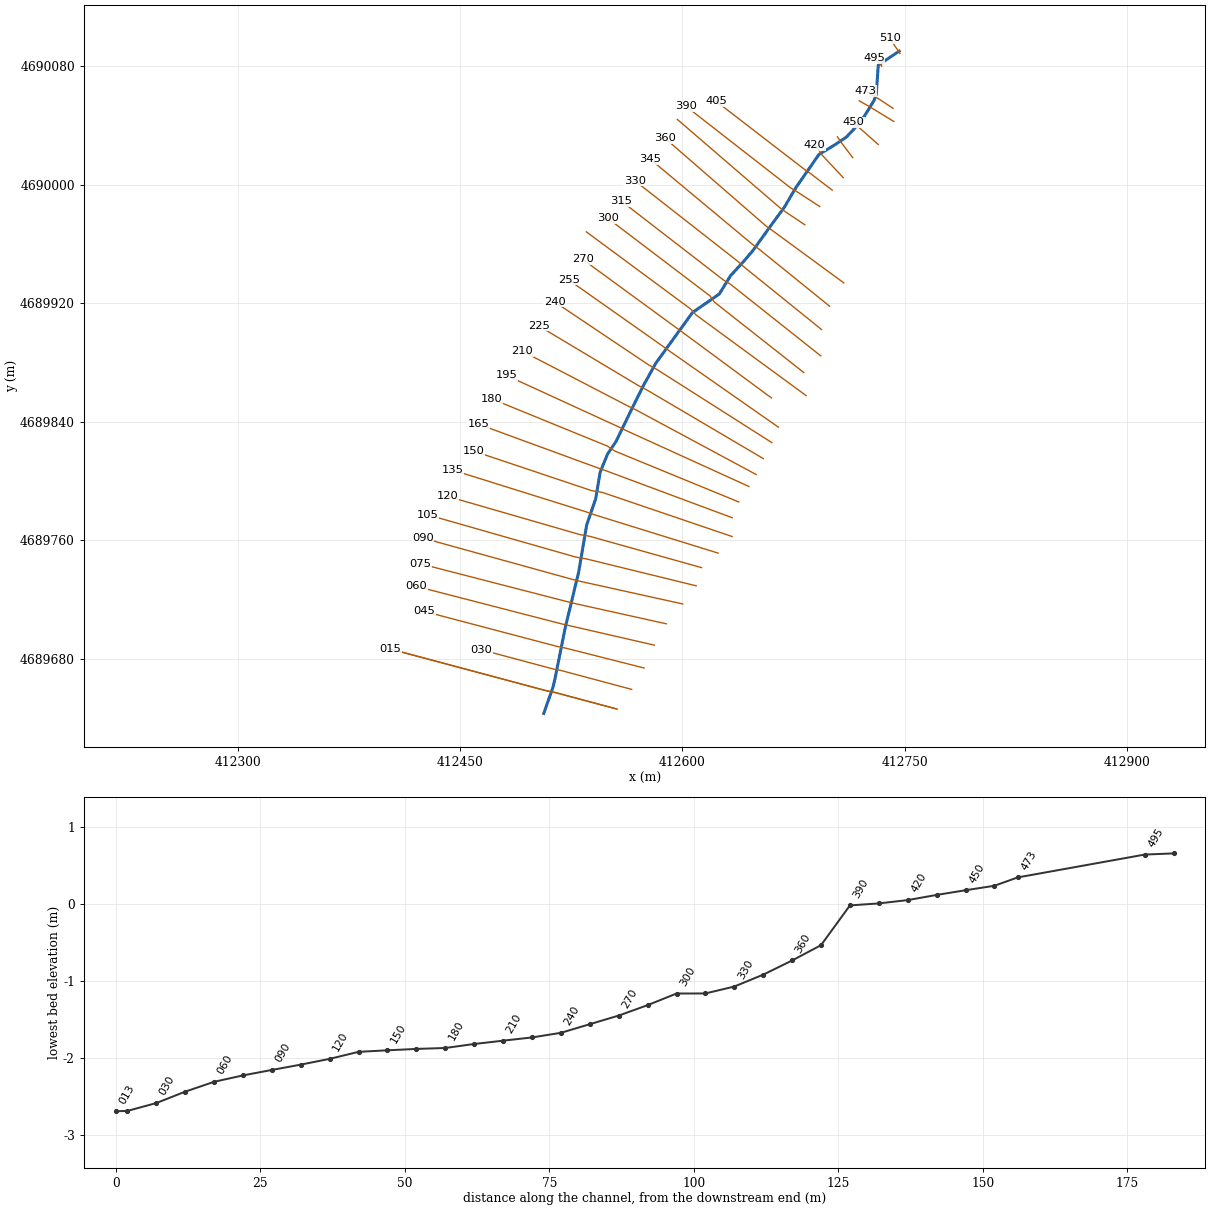
--- Castrillo01.prj (project) ---

Proj Title=Castrillo01
Current Plan=p01
Default Exp/Contr=0.3,0.1
SI Units
Geom File=g01
Flow File=f01
Plan File=p01
Y Axis Title=Elevation
X Axis Title(PF)=Main Channel Distance
X Axis Title(XS)=Station
BEGIN DESCRIPTION:
Cauce San Martín. Castrillo de Murcia.
END DESCRIPTION:
DSS Export Rating Curves= 0
DSS Export Rating Curve Sorted= 0
DSS Export Volume Flow Curves= 0
DXF OffsetX= 0
DXF OffsetY= 0
DXF ScaleX= 1
DXF ScaleY= 10

--- Castrillo01.p01 (plan) ---

Plan Title=PLANCASTRILLO01
Program Version=4.10
Short Identifier=PLAN01
Geom File=g01
Flow File=f01
Mixed Flow
K Sum by GR= 0
Std Step Tol= 0.003
Critical Tol= 0.003
Num of Std Step Trials= 20
Max Error Tol= 0.1
Flow Tol Ratio= 0.001
Split Flow NTrial= 30
Split Flow Tol= 0.006
Split Flow Ratio= 0.02
Log Output Level= 0
Friction Slope Method= 1
Unsteady Friction Slope Method= 2
Unsteady Bridges Friction Slope Method= 1
Calc Critical at every XS
Parabolic Critical Depth
Global Vel Dist= 0 , 0 , 0
Global Log Level= 0
CheckData=Verdadero
Encroach Param=-1 ,0,0, 0
Computation Interval=1HOUR
Output Interval=1HOUR
Run HTab= 0
Run UNet= 0
Run PostProcess= 0
Run WQNet= 0
UNET Theta= 1
UNET Theta Warmup= 1
UNET ZTol= 0.006
UNET ZSATol= 0.015
UNET MxIter= 20
UNET MaxInSteps= 0
UNET DtIC= 0
UNET DtMin= 0
UNET MaxCRTS= 20
UNET WFStab= 2
UNET SFStab= 1
UNET WFX= 1
UNET SFX= 1
UNET DSS MLevel= 4
UNET DZMax Abort= 30
UNET Convert EG Bridges= 0
UNET Use Existing IB Tables=-1
UNET Froude Reduction=Falso
UNET Froude Limit= 1
UNET Froude Power= 10
UNET Time Slicing=0,0, 5
UNET Junction Losses=0
Instantaneous Interval=1HOUR
Write IC File= 0
Write IC File at Sim End=0
Echo Input=Falso
Echo Parameters=Falso
Echo Output=Falso
Write Detailed= 0
WQ AD Non Conservative
WQ ULTIMATE=-1
WQ Max Comp Step=1HOUR
WQ Output Interval=15MIN
WQ Output Selected Increments= 0
WQ Output face flow=0
WQ Output face velocity=0
WQ Output face area=0
WQ Output face dispersion=0
WQ Output cell volume=0
WQ Output cell surface area=0
WQ Output cell continuity=0
WQ Output cumulative cell continuity=0
WQ Output face conc=0
WQ Output face dconc_dx=0
WQ Output face courant=0
WQ Output face peclet=0
WQ Output face adv mass=0
WQ Output face disp mass=0
WQ Output cell mass=0
WQ Output cell source sink temp=0
WQ Output cell source sink nsm=0
WQ Output MaxMinRange=-1
WQ Daily Max Min Mean=-1
WQ Daily Range=0
WQ Daily Time=0
WQ Create Restart=0
WQ Fixed Restart=0
WQ System Summary=0
WQ Use Fixed Temperature=0
Sorting and Armoring Iterations= 10
XS Update Threshold= 0.02
Hydraulics Update Threshold= 0.02
Energy Slope Method= 1
Volume Change Method= 0
XS Weighting Method= 0
Number of US Weighted Cross Sections= 1
Number of DS Weighted Cross Sections= 1
Upstream XS Weight=0.25
Main XS Weight=0.5
Downstream XS Weight=0.25
Number of DS XS's Weighted with US Boundary= 1
Upstream Boundary Weight= 1
Weight of XSs Associated with US Boundary= 0
Number of US XS's Weighted with DS Boundary= 1
Downstream Boundary Weight= 0.5
Weight of XSs Associated with DS Boundary= 0.5
Sediment Output Level= 4
Mass or Volume Output= 0
Output Increment Type= 1
Profile and TS Output Increment= 10
XS Output Flag= 0
XS Output Increment= 10
Disregard all LS=0
Disregard all Conn=0
Disregard all Breaches=0
Disregard all Pumps=0

--- Castrillo01.f01 (steady flow) ---

Flow Title=FLOWCASTRILLO01
Program Version=4.10
Number of Profiles= 3
Profile Names=M.C.O. (T=3.50),T=100,T=500
River Rch & RM=San Martin,Castrillo       ,510
     .41    4.86    8.46
River Rch & RM=San Martin,Castrillo       ,240
     .52    5.82   10.08
River Rch & RM=San Martin,Castrillo       ,045
     .58    6.27   10.85
River Rch & RM=San Martin,Castrillo       ,015
     .61    6.39   11.04
Boundary for River Rch & Prof#=San Martin,Castrillo       , 1
Up Type= 3
Up Slope=0.01
Dn Type= 3
Dn Slope=0.08
Boundary for River Rch & Prof#=San Martin,Castrillo       , 2
Up Type= 3
Up Slope=0.01
Dn Type= 3
Dn Slope=0.08
Boundary for River Rch & Prof#=San Martin,Castrillo       , 3
Up Type= 3
Up Slope=0.01
Dn Type= 3
Dn Slope=0.08
DSS Import GetInterval= 0
DSS Import GetPeak= 0
DSS Import FillOption= 0

--- Castrillo01.g01 (geometry) ---

Geom Title=GeoCastrillo01
Program Version=4.10

River Reach=San Martin      ,Castrillo
Reach XY= 30
     412746.2144    4690090.1726     412732.1171    4690080.7205
     412730.7738    4690061.3025     412729.2154    4690056.7985
     412720.6009     4690042.856     412710.7256    4690032.2926
     412702.7472    4690026.9159     412692.0622    4690020.4258
      412676.842     4689998.512     412673.2343    4689992.5604
     412668.8534    4689984.9712     412660.6571    4689973.8732
      412647.745    4689955.8851     412641.3294      4689948.35
     412632.4724    4689938.6956     412624.8426    4689926.3034
     412606.7106    4689913.7172      412581.966    4689879.5517
     412573.3502    4689863.9578     412568.5048    4689854.2625
     412555.0553    4689826.6276     412549.3943    4689818.2265
     412544.4283    4689805.9841      412541.425     4689788.146
     412535.2948    4689770.1933     412529.9825    4689738.7955
     412520.8514    4689700.9793     412514.0983    4689667.3088
     412512.5451    4689660.7389      412506.374    4689643.2956

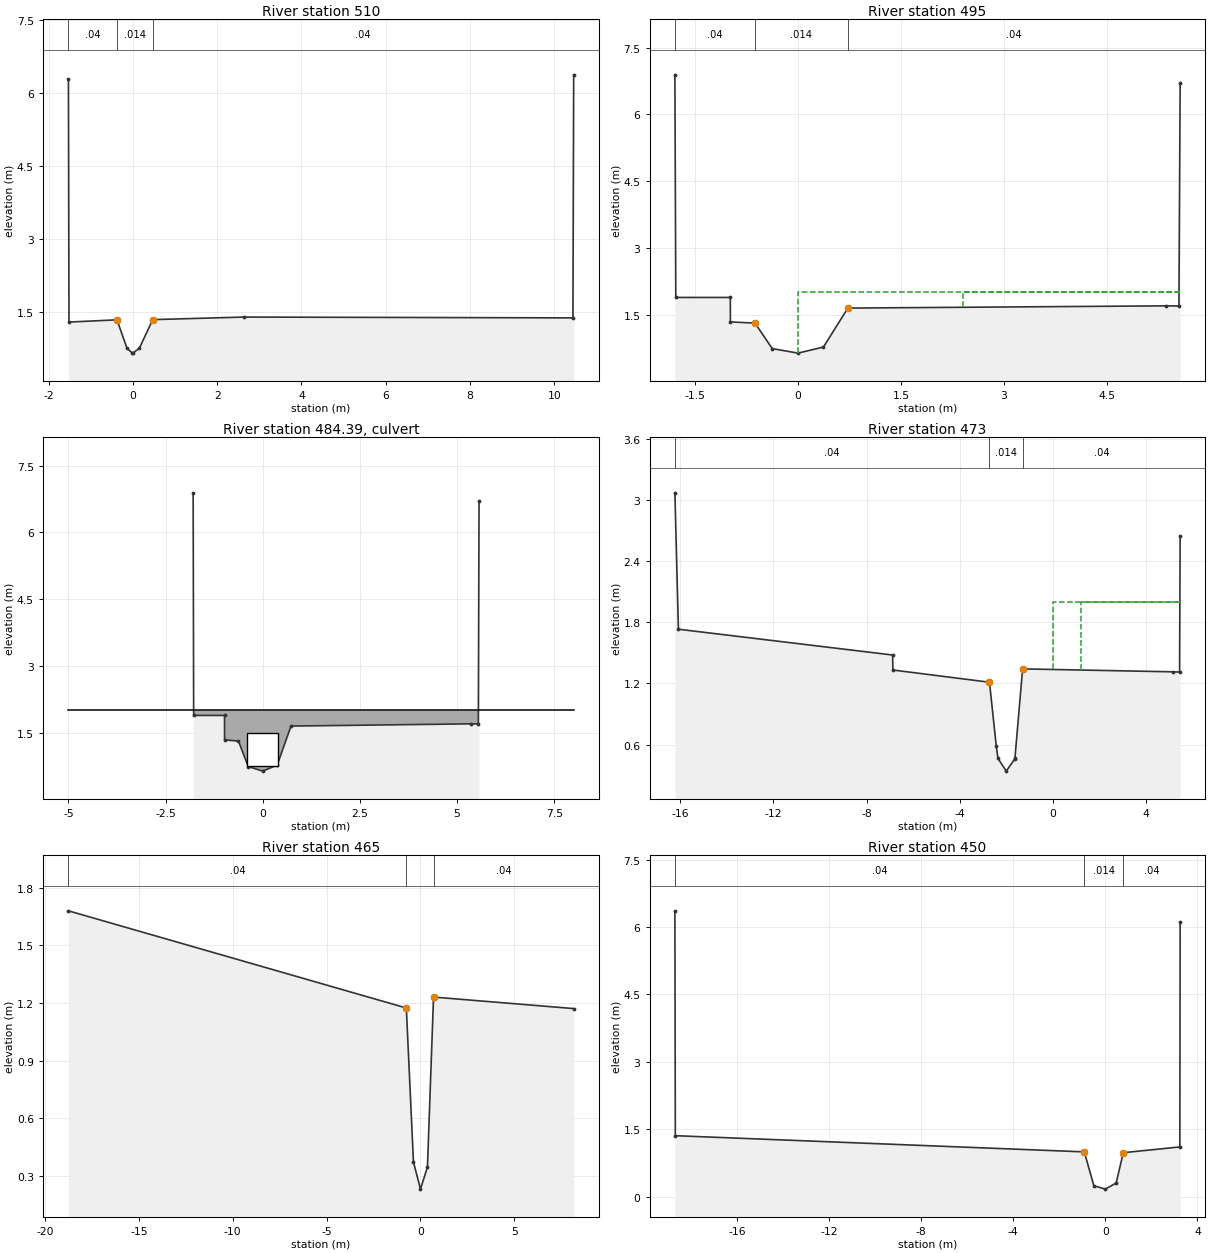
Type RM Length L Ch R = 1 ,510     ,5,5,5
XS GIS Cut Line= 5
412746.7699641994690088.59131366412746.1065426324690089.57278757
412745.8620787014690089.93445047412745.6176147714690090.29611338
412739.8677011864690098.80700908
#Sta/Elev= 11
  -1.529    6.29  -1.516    1.29   -.377   1.336   -.139    .751    -.01    .651
   -.001    .651    .153    .751    .472    1.34   2.632   1.393  10.442   1.376
   10.46   6.376
#Mann= 3 , 0 , 0
  -1.529     .04       0   -.377    .014       0    .472     .04       0
Bank Sta=-0.377,0.472
XS Rating Curve= 0 ,0
Exp/Cntr=0.8,0.6

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
Type RM Length L Ch R = 1 ,495     ,22,22,22
XS GIS Cut Line= 5
412734.4534686654690079.99599727412733.7913154524690080.99564241
  412733.40742564690081.57519654412733.0235357474690082.15475066
412729.1540964774690085.28199553
#Sta/Elev= 12
  -1.791   6.888  -1.778   1.887   -.984   1.887   -.983   1.337   -.625   1.311
   -.374    .738    .001    .636    .372    .773    .727   1.648   5.352   1.698
   5.547   1.696   5.565   6.696
#Mann= 3 , 0 , 0
  -1.791     .04       0   -.625    .014       0    .727     .04       0
#XS Ineff= 2 , 0
       0    -2.4       2     2.4       0       2
Permanent Ineff=
       F       F
Bank Sta=-0.625,0.727
XS Rating Curve= 0 ,0
Exp/Cntr=0.8,0.6

Type RM Length L Ch R = 2 ,484.39  ,,,
BEGIN DESCRIPTION:
ODT Aguas Arriba
END DESCRIPTION:
Bridge Culvert--1,0,-1,-1, 0
Deck Dist Width WeirC Skew NumUp NumDn MinLoCord MaxHiCord MaxSubmerge Is_Ogee
1.97,17.29,2.6,0, 2, 2, 2, , 0.98, 0, 0,0,,
      -5       8
       2       2
                
     -20       8
       2       2
                
BR Coef=-1 , 0 , 0 ,, 0 ,,,0.8,-1,,0,
WSPro=,,,, 1 ,,,, 0 ,,,, 0 ,,,,-1 ,-1 ,-1 , 0 , 0 , 0 , 0 , 0
Culvert=2,0.76,0.8,17.29,0.014,0.5,1,8,1,0.74,0,0.47,-2,Culvert #1  , 0 ,1.97
Culvert Bottom n=0.014
BC Design=,, 0 ,, 0 ,,,,,,
BC Use User HTab Curves=0
BC User HTab FreeFlow(D)= 0

Type RM Length L Ch R = 1 ,473     ,4,4,4
XS GIS Cut Line= 6
412742.085805578 4690051.5557765412737.5456600854690054.56999483
412734.2132906424690056.78236646412728.2615187424690060.50454545
412727.2419860454690061.14215107412723.6245893364690063.26164836
#Sta/Elev= 14
 -16.228   3.069 -16.077   1.731  -6.878   1.478  -6.866   1.331  -2.719   1.211
   -2.43     .59  -2.356    .465  -1.999    .339   -1.64    .456  -1.624    .471
  -1.296   1.342   5.171   1.313   5.444   1.311   5.469   2.644
#Mann= 3 , 0 , 0
 -16.228     .04       0  -2.719    .014       0  -1.296     .04       0
#XS Ineff= 2 , 0
       0    -5.2       2     1.2       0       2
Permanent Ineff=
       F       F
Bank Sta=-2.719,-1.296
XS Rating Curve= 0 ,0
Exp/Cntr=0.8,0.6

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
Type RM Length L Ch R = 1 ,465     ,5,5,5
XS GIS Cut Line= 5
412742.5890781334690042.72234817412727.2149805164690052.07804861
412726.5785234374690052.46535601412725.9420663574690052.85266342
412719.2607501284690056.63297814
#Sta/Elev= 7
  -18.75    1.68   -.753   1.174   -.373    .372    .001    .231    .372    .346
    .696   1.231   8.161   1.171
#Mann= 3 , 0 , 0
  -18.75     .04       0   -.753    .014       0    .696     .04       0
Bank Sta=-0.753,0.696
XS Rating Curve= 0 ,0
Exp/Cntr=0.3,0.1

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
Type RM Length L Ch R = 1 ,450     ,5,5,5
XS GIS Cut Line= 5
412732.1340536714690027.14345093412718.4316010374690039.26011098
412717.7953271754690039.85493796412717.1590533134690040.44976493
412715.3028163184690042.18508663
#Sta/Elev= 9
 -18.701    6.36 -18.682   1.361   -.914   1.001   -.498    .248    .001    .173
    .472     .31     .78    .983   3.237   1.111   3.251    6.11
#Mann= 3 , 0 , 0
 -18.701     .04       0   -.914    .014       0     .78     .04       0
Bank Sta=-0.914,0.78
XS Rating Curve= 0 ,0
Exp/Cntr=0.3,0.1

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
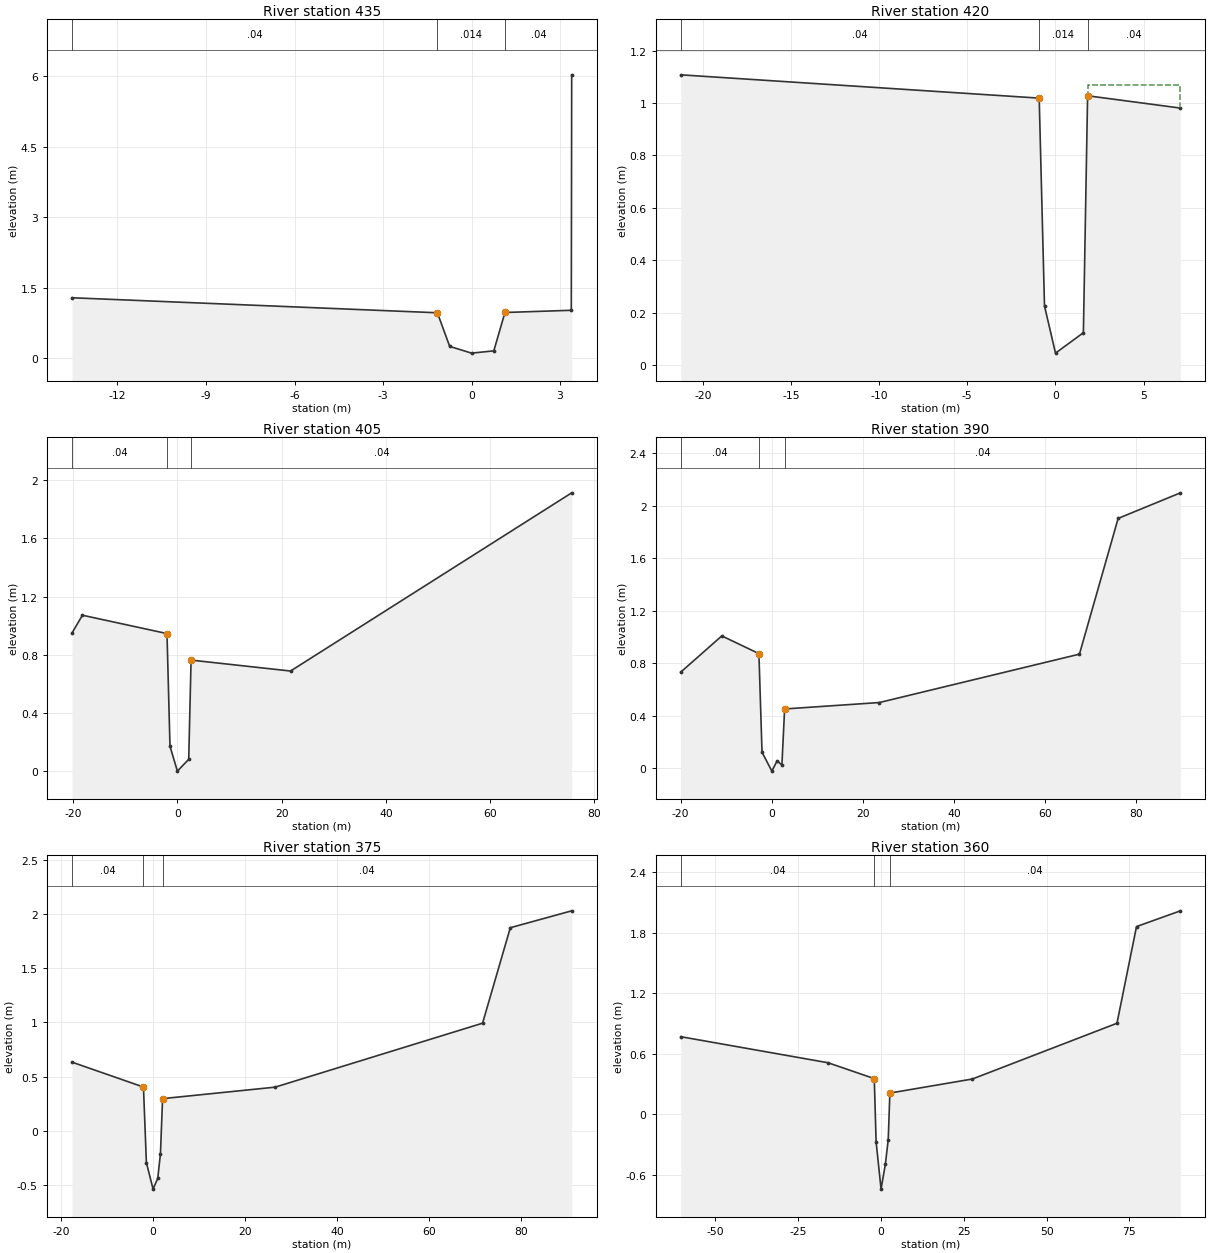
Type RM Length L Ch R = 1 ,435     ,5,5,5
XS GIS Cut Line= 5
412714.8383671374690018.31107654412707.1767731234690028.48114133
412706.5187487454690029.45757329412705.8607243674690030.43400524
412704.5607669664690032.36299145
#Sta/Elev= 8
  -13.54   1.288  -1.158    .969   -.741    .255   -.001    .112    .754     .16
   1.132    .975    3.38   1.022   3.394   6.023
#Mann= 3 , 0 , 0
  -13.54     .04       0  -1.158    .014       0   1.132     .04       0
Bank Sta=-1.158,1.132
XS Rating Curve= 0 ,0
Exp/Cntr=0.3,0.1

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
Type RM Length L Ch R = 1 ,420     ,5,5,5
XS GIS Cut Line= 5
412708.4601869884690004.79600761412694.1832835284690020.06277806
412693.4505627694690021.26909557412692.7178420094690022.47541309
412689.2669079254690026.64604814
#Sta/Elev= 7
  -21.25   1.108   -.924   1.019   -.623    .225    .001    .045   1.582    .123
   1.821   1.028   7.085    .981
#Mann= 3 , 0 , 0
  -21.25     .04       0   -.924    .014       0   1.821     .04       0
#XS Ineff= 2 , 0
                            1.82            1.07
Permanent Ineff=
       F       F
Bank Sta=-0.924,1.821
XS Rating Curve= 0 ,0
Exp/Cntr=0.3,0.1

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
Type RM Length L Ch R = 1 ,405     ,5,5,5
XS GIS Cut Line= 5
 412701.043238334689996.37588246 412686.141360464690007.73505458
412684.1894549654690009.09074789412682.237549469 4690010.4464412
412622.7492406764690056.28042805
#Sta/Elev= 9
 -20.213     .95 -18.218   1.072  -1.992    .946  -1.418    .173    .001    .002
   2.175    .083    2.63    .764  21.714    .689  75.657   1.912
#Mann= 3 , 0 , 0
 -20.213     .04       0  -1.992    .055       0    2.63     .04       0
Bank Sta=-1.992,2.63
XS Rating Curve= 0 ,0
Exp/Cntr=0.3,0.1

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
Type RM Length L Ch R = 1 ,390     ,5,5,5
XS GIS Cut Line= 5
412692.6352929234689985.29782112412678.1391531464689994.73032218
412675.5226207034689996.33542827412672.9060882594689997.94053436
412602.4733819514690052.85785886
#Sta/Elev= 12
 -19.989    .731 -10.975   1.007   -2.84    .872  -2.156     .12    .001   -.024
   1.149    .054   2.207    .023   2.799     .45  23.589    .499  67.489    .868
  75.984   1.903  89.649   2.098
#Mann= 3 , 0 , 0
 -19.989     .04       0   -2.84    .055       0   2.799     .04       0
Bank Sta=-2.84,2.799
XS Rating Curve= 0 ,0
Exp/Cntr=0.3,0.1

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
Type RM Length L Ch R = 1 ,375     ,5,5,5
XS GIS Cut Line= 5
 412682.505237064689973.03202761412669.2348135574689981.89497829
412667.5179411924689983.16295459412665.8010688284689984.43093089
412596.5427874034690044.07174554
#Sta/Elev= 11
 -17.606    .633  -2.088    .403  -1.451   -.295       0    -.54   1.019    -.44
   1.605   -.212   2.063    .296  26.504    .402  71.578    .993  77.609   1.875
  90.942   2.031
#Mann= 3 , 0 , 0
 -17.606     .04       0  -2.088    .055       0   2.063     .04       0
Bank Sta=-2.088,2.063
XS Rating Curve= 0 ,0
Exp/Cntr=0.3,0.1

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
Type RM Length L Ch R = 1 ,360     ,5,5,5
XS GIS Cut Line= 5
412708.8508069324689933.80409833412660.3771173864689969.31032217
412658.4050662584689970.71778292412656.4330151294689972.12524367
412588.3122833994690031.27826444
#Sta/Elev= 12
 -60.482     .77     -16    .512  -2.052    .355  -1.493   -.271       0   -.739
   1.285   -.495   2.165   -.249    2.66    .212  27.558    .351  71.232    .903
  77.128    1.86  90.392   2.016
#Mann= 3 , 0 , 0
 -60.482     .04       0  -2.052    .055       0    2.66     .04       0
Bank Sta=-2.052,2.66
XS Rating Curve= 0 ,0
Exp/Cntr=0.3,0.1

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
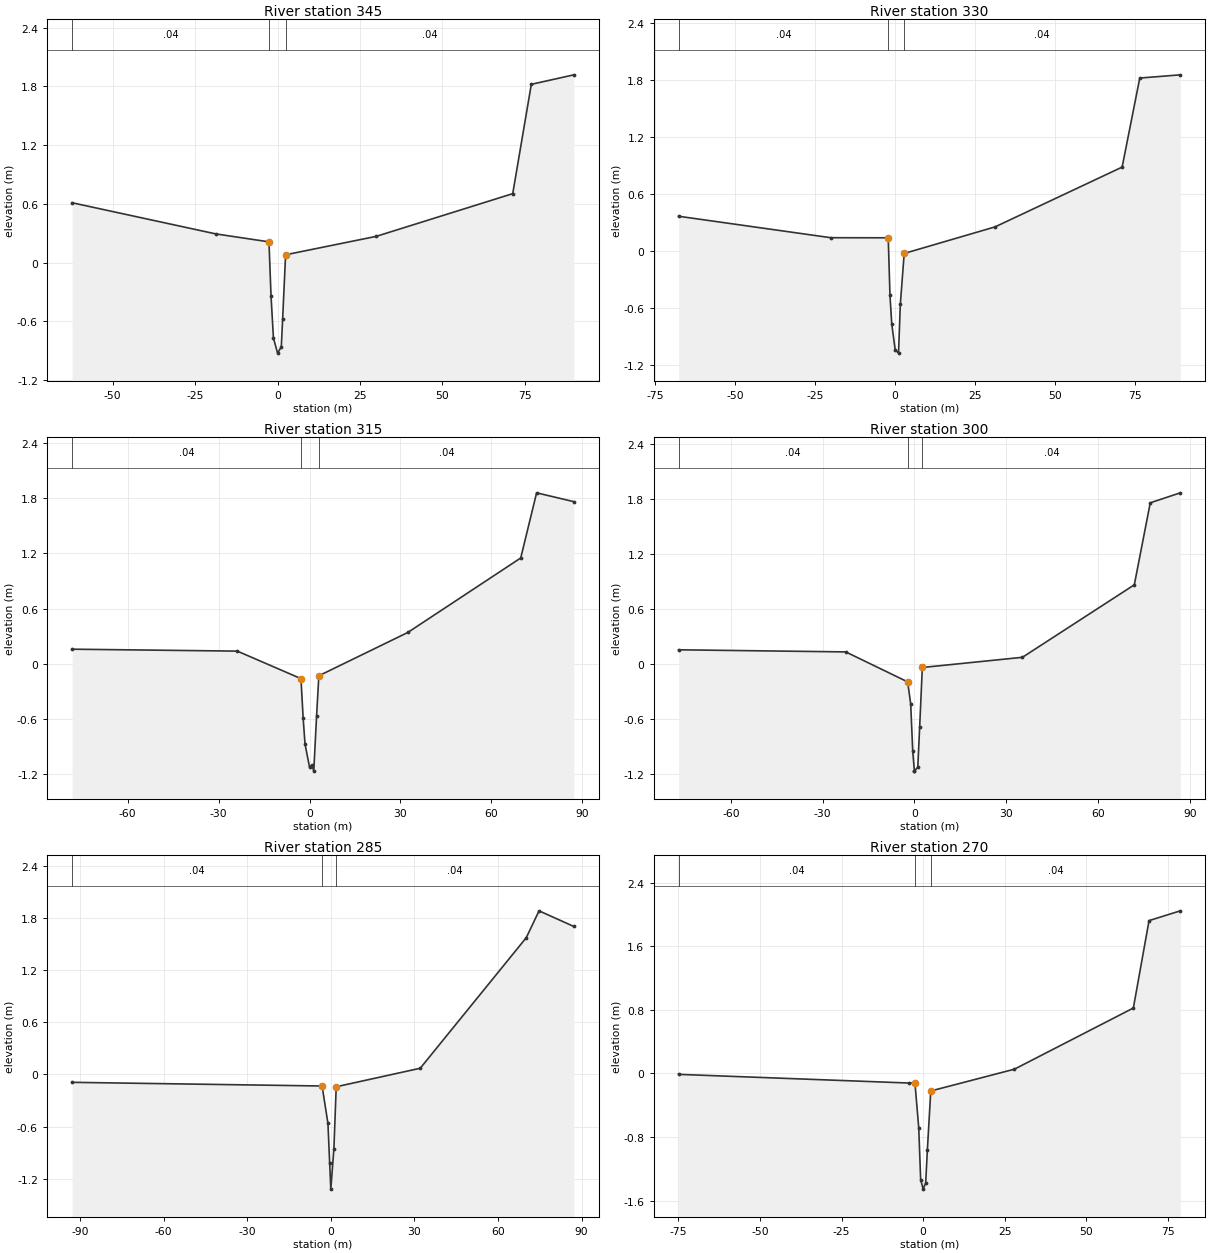
Type RM Length L Ch R = 1 ,345     ,5,5,5
XS GIS Cut Line= 5
412699.2425848444689918.07150022412651.5101462874689956.66744674
412649.4101360364689958.18672341412647.3101257864689959.70600008
412578.2471771334690017.24181476
#Sta/Elev= 13
 -62.301    .612 -18.721    .294  -2.609    .213  -1.988   -.339  -1.257   -.768
    .001   -.923   1.124    -.86   1.538   -.571   2.432    .081  29.919    .269
  71.305    .705  76.942   1.821  89.843   1.918
#Mann= 3 , 0 , 0
 -62.301     .04       0  -2.609    .055       0   2.432     .04       0
Bank Sta=-2.609,2.432
XS Rating Curve= 0 ,0
Exp/Cntr=0.3,0.1

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
Type RM Length L Ch R = 1 ,330     ,5,5,5
XS GIS Cut Line= 5
412693.8321417964689902.30012127412641.401689988 4689944.6357291
412639.5121806084689946.36917546412637.6226712274689948.10262183
412567.7215554244690002.82009484
#Sta/Elev= 13
   -67.7    .365 -20.132    .139  -2.169    .138  -1.628   -.465  -1.074   -.768
   -.001  -1.041   1.049  -1.077   1.613   -.562   2.818   -.027  31.227    .253
  70.953    .883   76.46   1.821  89.141   1.855
#Mann= 3 , 0 , 0
   -67.7     .04       0  -2.169    .055       0   2.818     .04       0
Bank Sta=-2.169,2.818
XS Rating Curve= 0 ,0
Exp/Cntr=0.3,0.1

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
Type RM Length L Ch R = 1 ,315     ,5,5,5
XS GIS Cut Line= 5
412693.2512033284689884.57697641412632.427213189 4689932.8379752
412629.8448254624689934.42793516412627.2624377354689936.01789513
412558.8122865574689988.94113607
#Sta/Elev= 14
 -78.318    .158 -23.813    .137  -2.814   -.162  -2.098   -.589  -1.477   -.872
       0  -1.122    .828  -1.102   1.407  -1.167   2.339   -.566   3.084   -.131
   32.45     .34  69.689   1.149   74.93   1.857  87.222   1.761
#Mann= 3 , 0 , 0
 -78.318     .04       0  -2.814    .055       0   3.084     .04       0
Bank Sta=-2.814,3.084
XS Rating Curve= 0 ,0
Exp/Cntr=0.3,0.1

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
Type RM Length L Ch R = 1 ,300     ,5,5,5
XS GIS Cut Line= 5
412681.8741032464689873.26414786412621.4190926784689920.92076783
412620.0122649014689922.94295562412618.605437125 4689924.9651434
412549.5528211684689977.40648393
#Sta/Elev= 14
  -77.06    .156 -22.436    .133  -2.202   -.194  -1.207   -.435   -.548   -.947
    .002  -1.168    .014  -1.165   1.106  -1.126   1.721   -.687   2.589   -.037
  35.302    .074  71.868    .865  77.081    1.76  86.907   1.869
#Mann= 3 , 0 , 0
  -77.06     .04       0  -2.202    .055       0   2.589     .04       0
Bank Sta=-2.202,2.589
XS Rating Curve= 0 ,0
Exp/Cntr=0.3,0.1

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
Type RM Length L Ch R = 1 ,285     ,5,5,5
XS GIS Cut Line= 5
412683.4703123184689857.69572231412609.0639773464689912.20223287
412607.3375984694689914.15141371412605.6112195914689916.10059455
412535.1030924484689968.24248054
#Sta/Elev= 12
 -92.823   -.091  -3.572   -.133  -3.131   -.133   -1.03   -.563   -.418  -1.016
   -.001  -1.319   1.106   -.855   1.933   -.142  32.087    .071  70.147   1.573
  74.717   1.881  87.209   1.701
#Mann= 3 , 0 , 0
 -92.823     .04       0  -3.131    .055       0   1.933     .04       0
Bank Sta=-3.131,1.933
XS Rating Curve= 0 ,0
Exp/Cntr=0.3,0.1

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
Type RM Length L Ch R = 1 ,270     ,5,5,5
XS GIS Cut Line= 5
 412660.04205264 4689856.1267959412600.126269486 4689900.3816704
 412598.109921714689901.84202424412596.0935739354689903.30237808
412532.5972828524689949.70412261
#Sta/Elev= 13
 -74.944   -.011  -4.386    -.12   -2.51    -.12  -1.351   -.684   -.762  -1.334
   -.001  -1.454    .773  -1.376   1.284   -.965   2.332    -.22  27.966    .054
  64.414    .823  69.222   1.922  78.808   2.045
#Mann= 3 , 0 , 0
 -74.944     .04       0   -2.51    .055       0   2.332     .04       0
Bank Sta=-2.51,2.332
XS Rating Curve= 0 ,0
Exp/Cntr=0.3,0.1

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
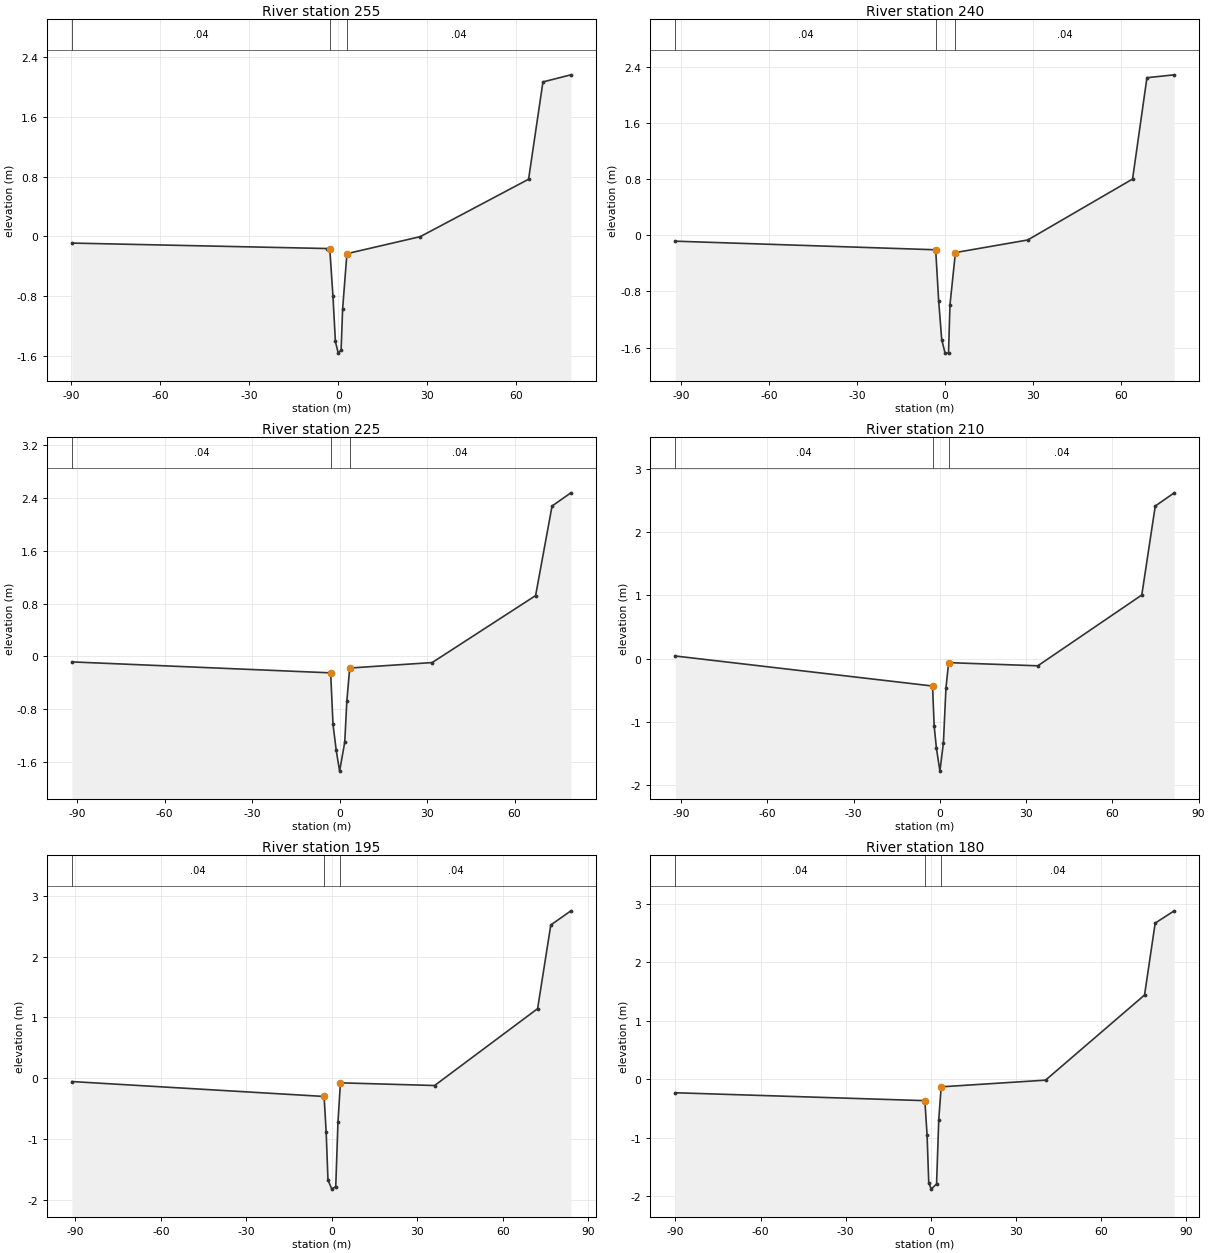
Type RM Length L Ch R = 1 ,255     ,5,5,5
XS GIS Cut Line= 5
412664.7217038094689836.41213098412591.4696712564689887.60530412
412589.061880577 4689889.3491632412586.6540898984689891.09302227
412523.1836776964689935.82005464
#Sta/Elev= 13
 -89.757   -.091  -3.936   -.164  -2.853   -.164  -1.768   -.807   -.951   -1.41
    .002  -1.566    .972  -1.527    1.48   -.976   2.929   -.233  27.641   -.005
  64.176    .765  69.017   2.069  78.435   2.164
#Mann= 3 , 0 , 0
 -89.757     .04       0  -2.853    .055       0   2.929     .04       0
Bank Sta=-2.853,2.929
XS Rating Curve= 0 ,0
Exp/Cntr=0.3,0.1

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
Type RM Length L Ch R = 1 ,240     ,5,5,5
XS GIS Cut Line= 5
412660.3203847674689825.98601895412583.3779817814689874.96037336
 412580.356524364689876.63867948412577.3350669394689878.31698561
412513.6712413284689921.00012312
#Sta/Elev= 13
 -91.889   -.085  -3.487   -.207  -3.197   -.208  -2.185    -.93   -1.14  -1.485
    .002  -1.678   1.171  -1.677   1.676   -.987   3.525   -.247  28.163   -.068
  63.872    .799  68.768   2.241   78.06   2.282
#Mann= 3 , 0 , 0
 -91.889     .04       0  -3.197    .055       0   3.525     .04       0
Bank Sta=-3.197,3.525
XS Rating Curve= 0 ,0
Exp/Cntr=0.3,0.1

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
Type RM Length L Ch R = 1 ,225     ,5,5,5
XS GIS Cut Line= 5
412654.523158715 4689815.2314726412575.9158608854689861.57145494
412572.9310638724689863.11913849 412569.946266864689864.66682204
412503.0147026654689904.75366093
#Sta/Elev= 12
 -91.805   -.084  -3.071    -.25  -2.263  -1.029  -1.172  -1.419   -.001  -1.738
   1.768  -1.297   2.472   -.682   3.468   -.177  31.757   -.094  67.235     .92
  72.874   2.276  79.335   2.476
#Mann= 3 , 0 , 0
 -91.805     .04       0  -3.071    .055       0   3.468     .04       0
Bank Sta=-3.071,3.468
XS Rating Curve= 0 ,0
Exp/Cntr=0.3,0.1

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
Type RM Length L Ch R = 1 ,210     ,5,5,5
XS GIS Cut Line= 5
412649.7502114734689804.46268949412568.6963289124689848.03662104
412566.1043832664689849.28713133 412563.512437624689850.53764161
412491.886435358  4689887.730889
#Sta/Elev= 12
  -92.05    .041  -2.563   -.434  -1.993  -1.067  -1.206   -1.42    .002   -1.78
   1.218  -1.332   2.107   -.461   3.034   -.064  34.058   -.114  70.238   1.006
   74.92   2.413  81.516   2.622
#Mann= 3 , 0 , 0
  -92.05     .04       0  -2.563    .055       0   3.034     .04       0
Bank Sta=-2.563,3.034
XS Rating Curve= 0 ,0
Exp/Cntr=0.3,0.1

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
Type RM Length L Ch R = 1 ,195     ,5,5,5
XS GIS Cut Line= 5
412644.8316387144689796.39733099 412562.001833534689834.12236097
412559.3542832834689835.41726516412556.7067330374689836.71216935
412481.0841461064689871.40991487
#Sta/Elev= 12
 -91.202   -.055  -2.695     -.3  -1.973   -.876  -1.331   -1.67    .005  -1.823
   1.397   -1.78   2.177   -.724   3.037   -.076  36.109    -.12  72.263   1.143
  76.894   2.518  83.946   2.751
#Mann= 3 , 0 , 0
 -91.202     .04       0  -2.695    .055       0   3.037     .04       0
Bank Sta=-2.695,3.037
XS Rating Curve= 0 ,0
Exp/Cntr=0.3,0.1

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
Type RM Length L Ch R = 1 ,180     ,5,5,5
XS GIS Cut Line= 5
412637.9649352454689785.95723549412554.3555044244689820.29745901
412551.9032625754689821.94987846412549.4510207264689823.60229792
412471.3001199984689855.50605859
#Sta/Elev= 12
  -90.04    -.23  -2.145   -.365  -1.362   -.948   -.772  -1.764    .085  -1.875
    1.98  -1.786   2.755   -.687   3.606   -.129  40.373   -.015  75.238   1.438
  78.989   2.666  85.691   2.875
#Mann= 3 , 0 , 0
  -90.04     .04       0  -2.145    .055       0   3.606     .04       0
Bank Sta=-2.145,3.606
XS Rating Curve= 0 ,0
Exp/Cntr=0.3,0.1

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
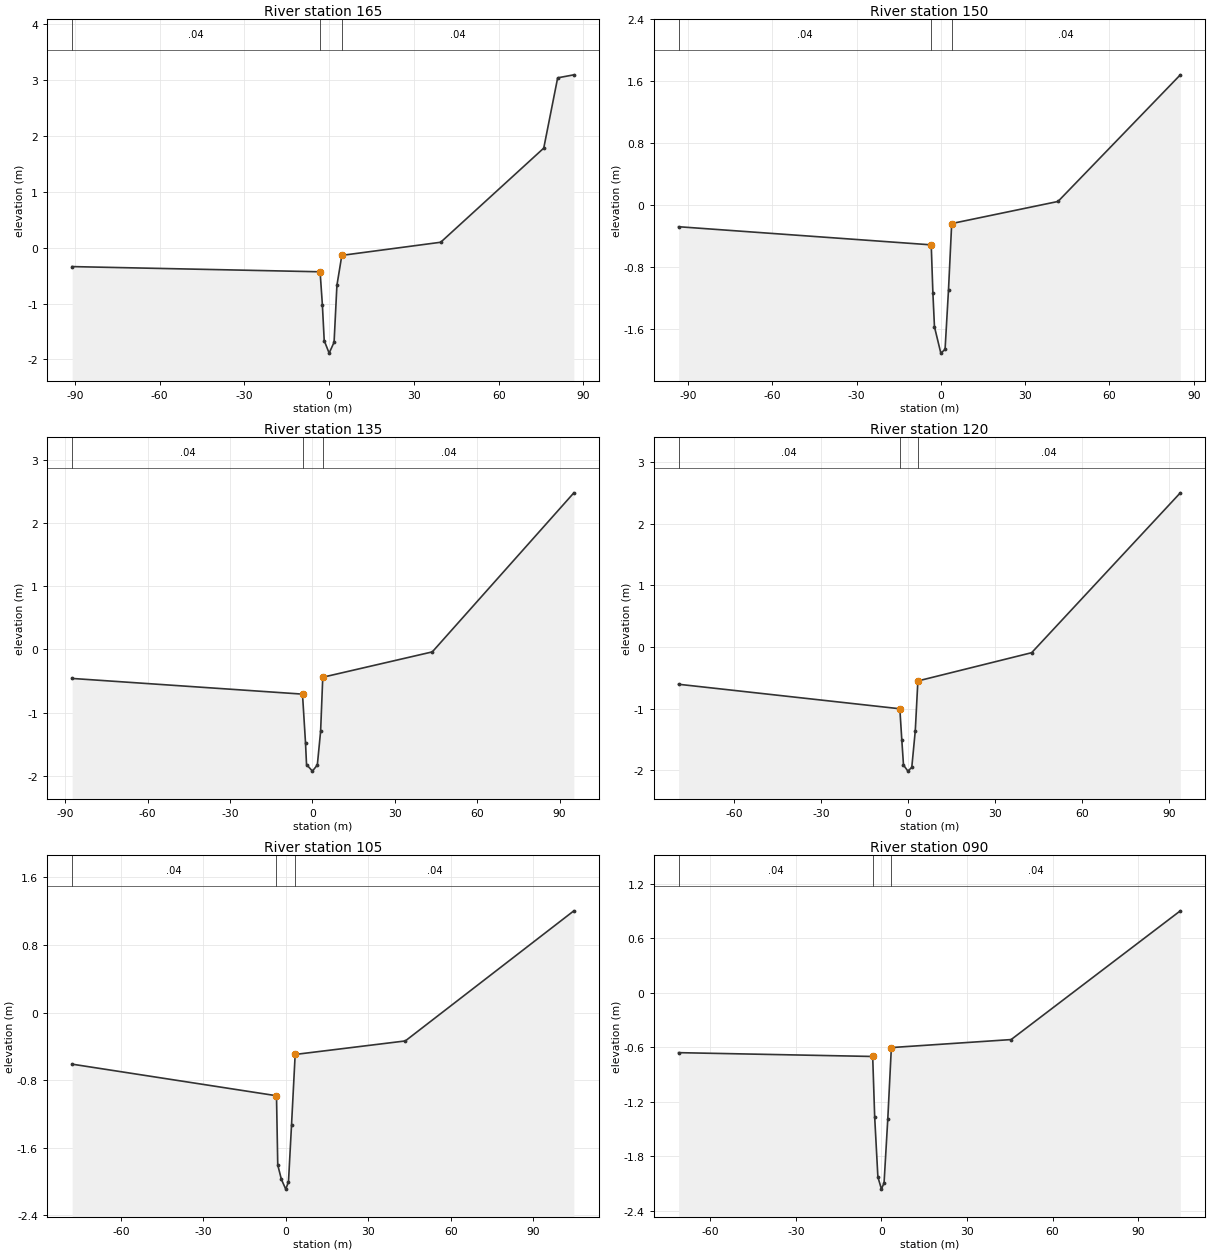
Type RM Length L Ch R = 1 ,165     ,5,5,5
XS GIS Cut Line= 5
412633.5732402444689775.29525421412549.0110595234689806.77801807
412545.2837612254689808.09302036412541.5564629284689809.40802265
412462.2756861754689838.45312304
#Sta/Elev= 12
 -90.943   -.337  -3.198    -.43  -2.396  -1.019  -1.741  -1.663    .003  -1.887
   1.749  -1.692    2.75   -.674   4.489   -.136  39.472    .099  75.939   1.785
  80.863   3.044  86.595   3.098
#Mann= 3 , 0 , 0
 -90.943     .04       0  -3.198    .055       0   4.489     .04       0
Bank Sta=-3.198,4.489
XS Rating Curve= 0 ,0
Exp/Cntr=0.3,0.1

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
Type RM Length L Ch R = 1 ,150     ,5,5,5
XS GIS Cut Line= 5
412633.4698509364689762.64138446412545.937895745 4689792.3954308
412542.2451298114689793.01716092412538.5523638774689793.63889103
412459.2199294784689820.23127159
#Sta/Elev= 10
 -93.318   -.274  -3.416   -.508  -2.819  -1.132  -2.262  -1.566    .002  -1.905
   1.511  -1.857   2.739  -1.084   3.867   -.233    41.7    .052  85.231   1.686
#Mann= 3 , 0 , 0
 -93.318     .04       0  -3.416    .055       0   3.867     .04       0
Bank Sta=-3.416,3.867
XS Rating Curve= 0 ,0
Exp/Cntr=0.3,0.1

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
Type RM Length L Ch R = 1 ,135     ,5,5,5
XS GIS Cut Line= 5
412624.0419217224689751.43853409412541.6281754244689776.99663782
412538.0366571924689778.22301186 412534.445138964689779.44938589
412444.695028132 4689807.5512465
#Sta/Elev= 10
 -87.525   -.459  -3.618   -.707  -2.526  -1.475  -2.149  -1.821    .002  -1.925
   1.787  -1.827   2.978  -1.295   3.763    -.44  43.657   -.039  95.217   2.477
#Mann= 3 , 0 , 0
 -87.525     .04       0  -3.618    .055       0   3.763     .04       0
Bank Sta=-3.618,3.763
XS Rating Curve= 0 ,0
Exp/Cntr=0.3,0.1

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
Type RM Length L Ch R = 1 ,120     ,5,5,5
XS GIS Cut Line= 5
412612.8265700564689741.65823931 412537.290351624689762.81670011
412534.136997295 4689763.3502268412530.9836429714689763.88375349
412441.5850022434689789.70653536
#Sta/Elev= 10
 -79.067   -.605  -2.786  -1.003  -2.101  -1.513  -1.524  -1.918    .002  -2.016
   1.332  -1.955    2.54  -1.359   3.434   -.551  42.665   -.092  93.922   2.505
#Mann= 3 , 0 , 0
 -79.067     .04       0  -2.786    .055       0   3.434     .04       0
Bank Sta=-2.786,3.434
XS Rating Curve= 0 ,0
Exp/Cntr=0.3,0.1

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
Type RM Length L Ch R = 1 ,105     ,5,5,5
XS GIS Cut Line= 5
 412609.26747191 4689729.3705248412535.0075656674689747.55844608
412531.5637174724689748.14112241412528.1198692764689748.72379874
412427.8662873174689777.35716625
#Sta/Elev= 10
 -77.706   -.611  -3.359   -.985    -2.9  -1.805   -1.59  -1.974    .001  -2.091
    .998  -2.007   2.115  -1.329   3.434   -.496    43.5   -.336 104.822   1.205
#Mann= 3 , 0 , 0
 -77.706     .04       0  -3.359    .055       0   3.434     .04       0
Bank Sta=-3.359,3.434
XS Rating Curve= 0 ,0
Exp/Cntr=0.3,0.1

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
Type RM Length L Ch R = 1 ,090     ,5,5,5
XS GIS Cut Line= 5
412600.1549585984689717.13384003412531.8380514454689732.22007232
412528.5705091584689733.01874568 412525.302966874689733.81741904
412424.9042887714689761.56566551
#Sta/Elev= 10
 -71.098   -.658  -3.064     -.7  -2.363  -1.368  -1.242  -2.026    .002   -2.16
    .924  -2.091   2.236  -1.384   3.478   -.602  45.461   -.514 104.769    .903
#Mann= 3 , 0 , 0
 -71.098     .04       0  -3.064    .055       0   3.478     .04       0
Bank Sta=-3.064,3.478
XS Rating Curve= 0 ,0
Exp/Cntr=0.3,0.1

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
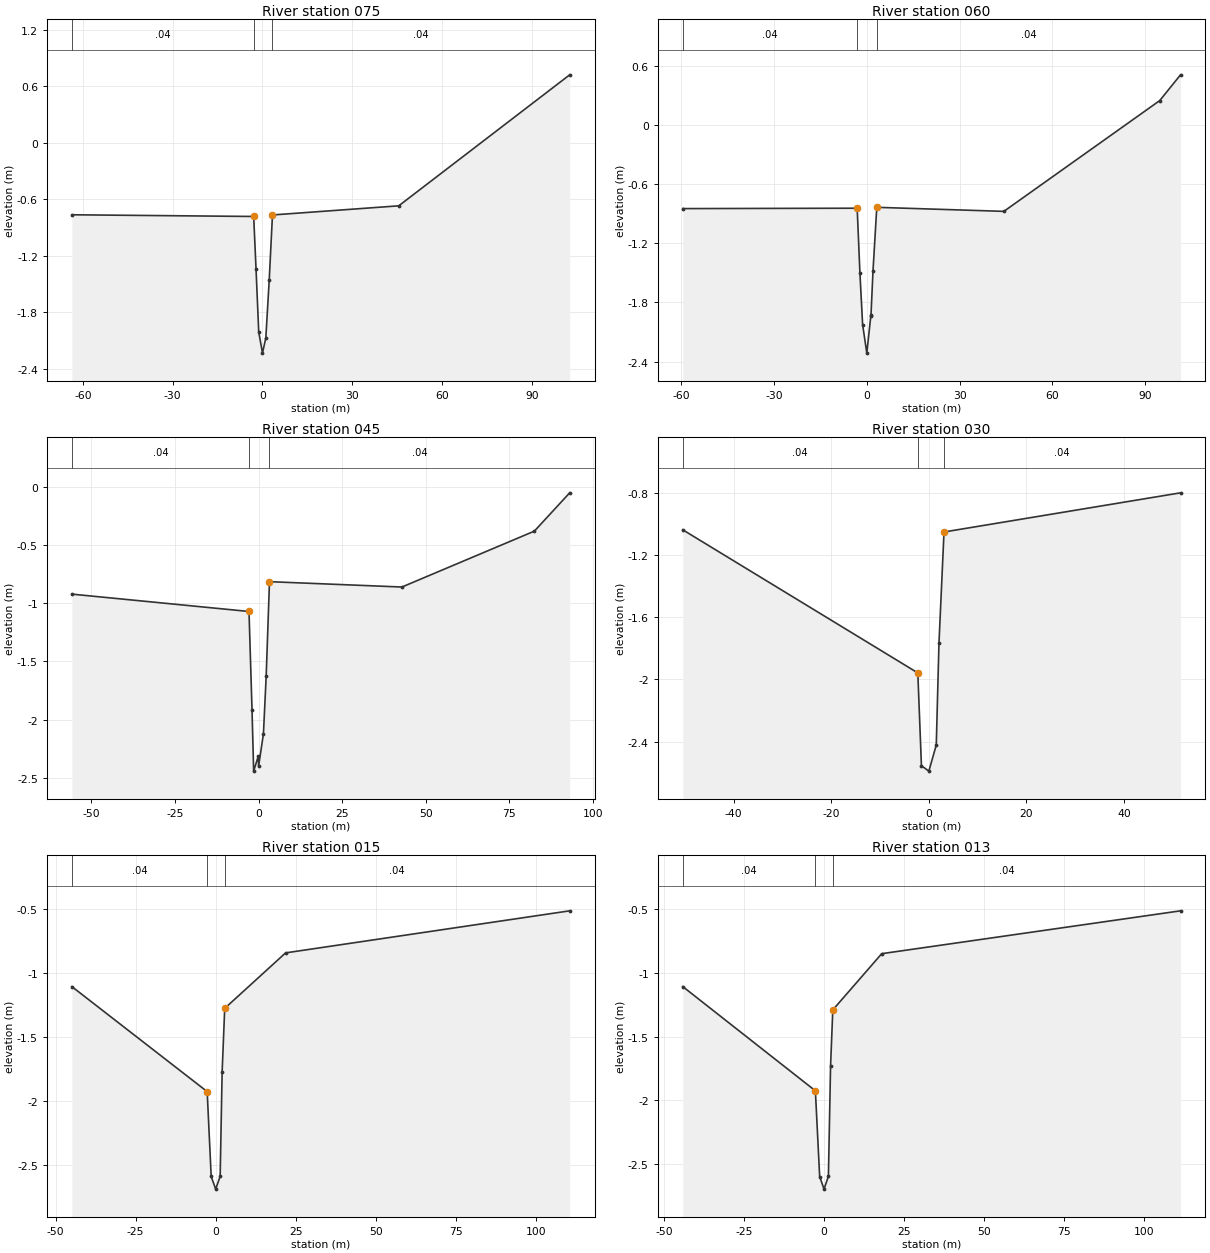
Type RM Length L Ch R = 1 ,075     ,5,5,5
XS GIS Cut Line= 5
412589.0308592654689703.74166924412528.0436717914689717.26815825
412524.9079898224689718.03460148412521.772307854 4689718.8010447
412422.8490495644689744.30653318
#Sta/Elev= 10
 -63.693   -.764  -2.946   -.782  -2.149  -1.344  -1.262  -2.005   -.001  -2.231
   1.118  -2.068   2.249  -1.457   3.332   -.766  45.546   -.669 102.674     .72
#Mann= 3 , 0 , 0
 -63.693     .04       0  -2.946    .055       0   3.332     .04       0
Bank Sta=-2.946,3.332
XS Rating Curve= 0 ,0
Exp/Cntr=0.3,0.1

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
Type RM Length L Ch R = 1 ,060     ,5,5,5
XS GIS Cut Line= 5
412580.991154599 4689689.3394419412524.5082415474689702.29929257
412521.3342884754689703.02914136412518.1603354034689703.75899014
412420.4394308954689728.99334196
#Sta/Elev= 12
 -59.462   -.849  -3.109   -.845  -2.223  -1.502  -1.354  -2.024    .001  -2.314
   1.311  -1.933   1.348  -1.932   2.009  -1.477   3.225   -.836  44.286   -.877
  94.654    .246 101.369    .507
#Mann= 3 , 0 , 0
 -59.462     .04       0  -3.109    .055       0   3.225     .04       0
Bank Sta=-3.109,3.225
XS Rating Curve= 0 ,0
Exp/Cntr=0.3,0.1

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
Type RM Length L Ch R = 1 ,045     ,5,5,5
XS GIS Cut Line= 5
412574.0561881944689673.92610395412521.2759785424689687.29931682
 412518.190157674689687.92856225412515.1043367984689688.55780769
412425.8415031494689712.08339482
#Sta/Elev= 12
 -55.814   -.922  -2.867  -1.071   -1.96  -1.917  -1.474  -2.442   -.087  -2.313
    .002    -2.4   1.448  -2.122   2.272  -1.626   3.258   -.815  42.853   -.861
  82.464   -.381  93.024   -.052
#Mann= 3 , 0 , 0
 -55.814     .04       0  -2.867    .055       0   3.258     .04       0
Bank Sta=-2.867,3.258
XS Rating Curve= 0 ,0
Exp/Cntr=0.3,0.1

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
Type RM Length L Ch R = 1 ,030     ,5,5,5
XS GIS Cut Line= 5
412565.739206719 4689659.4777134412517.8786698574689672.27462448
  412515.16793874689672.80241916412512.4572075424689673.33021384
412464.299930099 4689686.2156409
#Sta/Elev= 8
 -50.437  -1.037  -2.261  -1.958  -1.519  -2.555    .002   -2.59   1.522  -2.422
   2.076  -1.767    3.11  -1.051  51.587   -.799
#Mann= 3 , 0 , 0
 -50.437     .04       0  -2.261    .055       0    3.11     .04       0
Bank Sta=-2.261,3.11
XS Rating Curve= 0 ,0
Exp/Cntr=0.8,0.6

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
Type RM Length L Ch R = 1 ,015     ,2,2,2
XS GIS Cut Line= 6
412555.9941113044689646.15428138412513.481700507 4689657.5212149
 412510.770969354689658.04900958412508.0602381924689658.57680426
412459.9029607494689671.46223132412402.9127640354689686.71107972
#Sta/Elev= 9
 -44.901  -1.108  -2.654  -1.929    -1.4  -2.593    .002  -2.692   1.405  -2.592
   2.014  -1.778   2.823  -1.278  21.841   -.844 110.582   -.515
#Mann= 3 , 0 , 0
 -44.901     .04       0  -2.654    .055       0   2.823     .04       0
Bank Sta=-2.654,2.823
XS Rating Curve= 0 ,0
Exp/Cntr=0.8,0.6

Type RM Length L Ch R = 1 ,013     ,3.5,3.5,3.5
XS GIS Cut Line= 6
412555.200004896 4689646.3666089412513.481700507 4689657.5212149
 412510.770969354689658.04900958412508.0602381924689658.57680426
412459.9029607494689671.46223132412402.2703615664689686.88296714
#Sta/Elev= 9
 -44.079  -1.108  -2.698  -1.925  -1.361  -2.597    .002  -2.696   1.367  -2.596
   2.043  -1.729   2.739  -1.291      18    -.85 111.247   -.514
#Mann= 3 , 0 , 0
 -44.079     .04       0  -2.698    .055       0   2.739     .04       0
Bank Sta=-2.698,2.739
XS Rating Curve= 0 ,0
Exp/Cntr=0.8,0.6

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