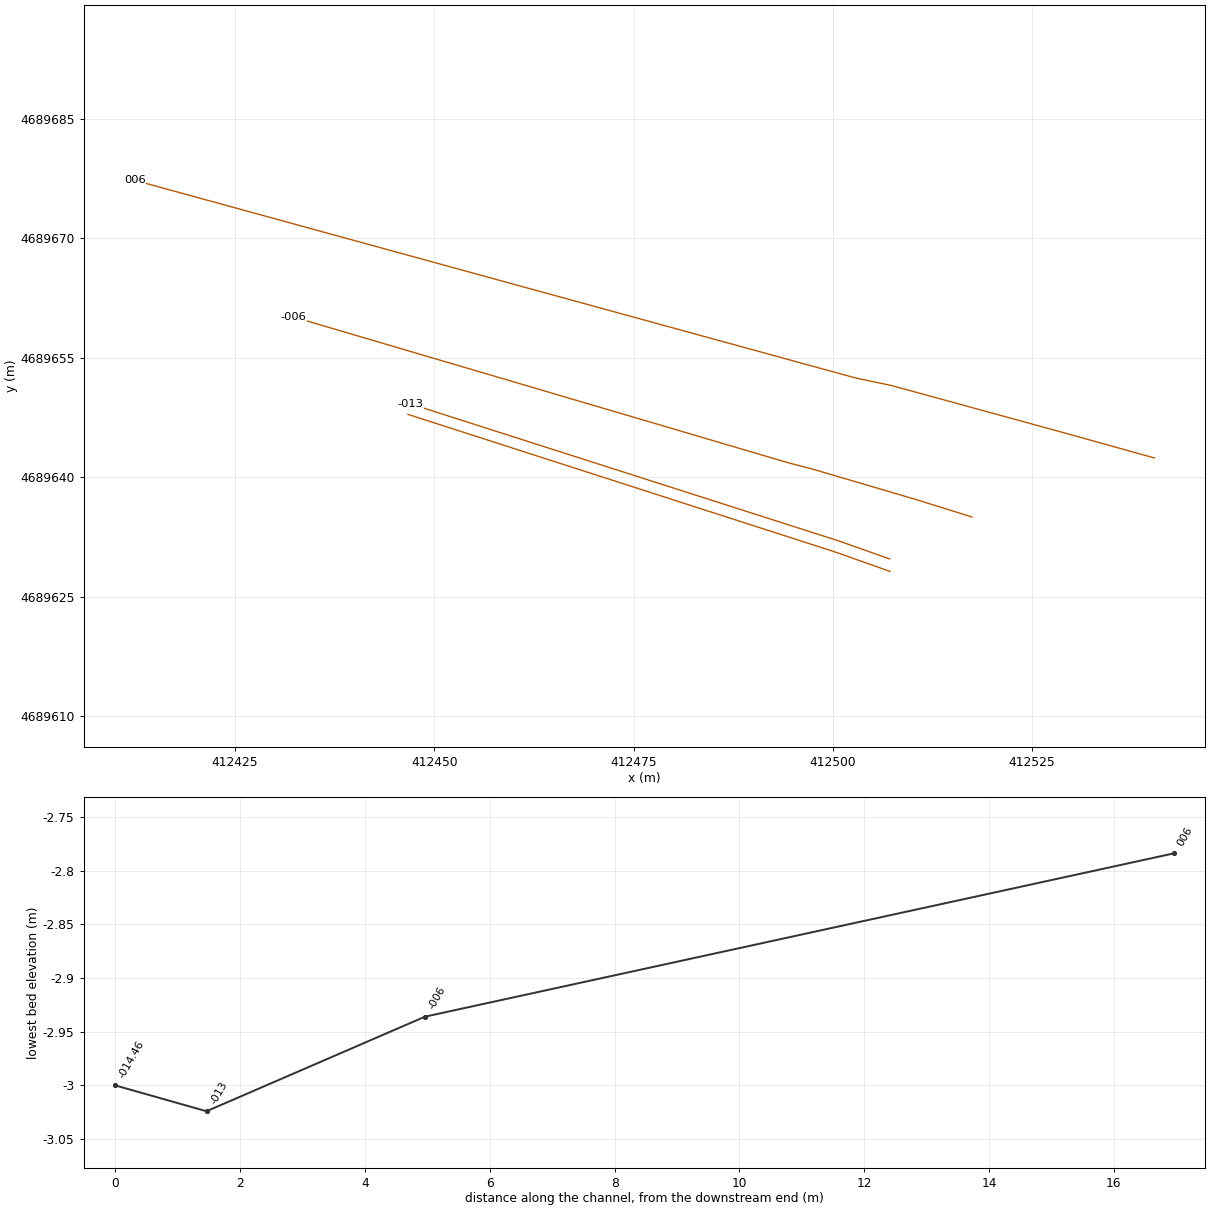
HEC-RAS study Castrillo01.prj: Castrillo01

--- Castrillo01.g01 (geometry) --- (continued)

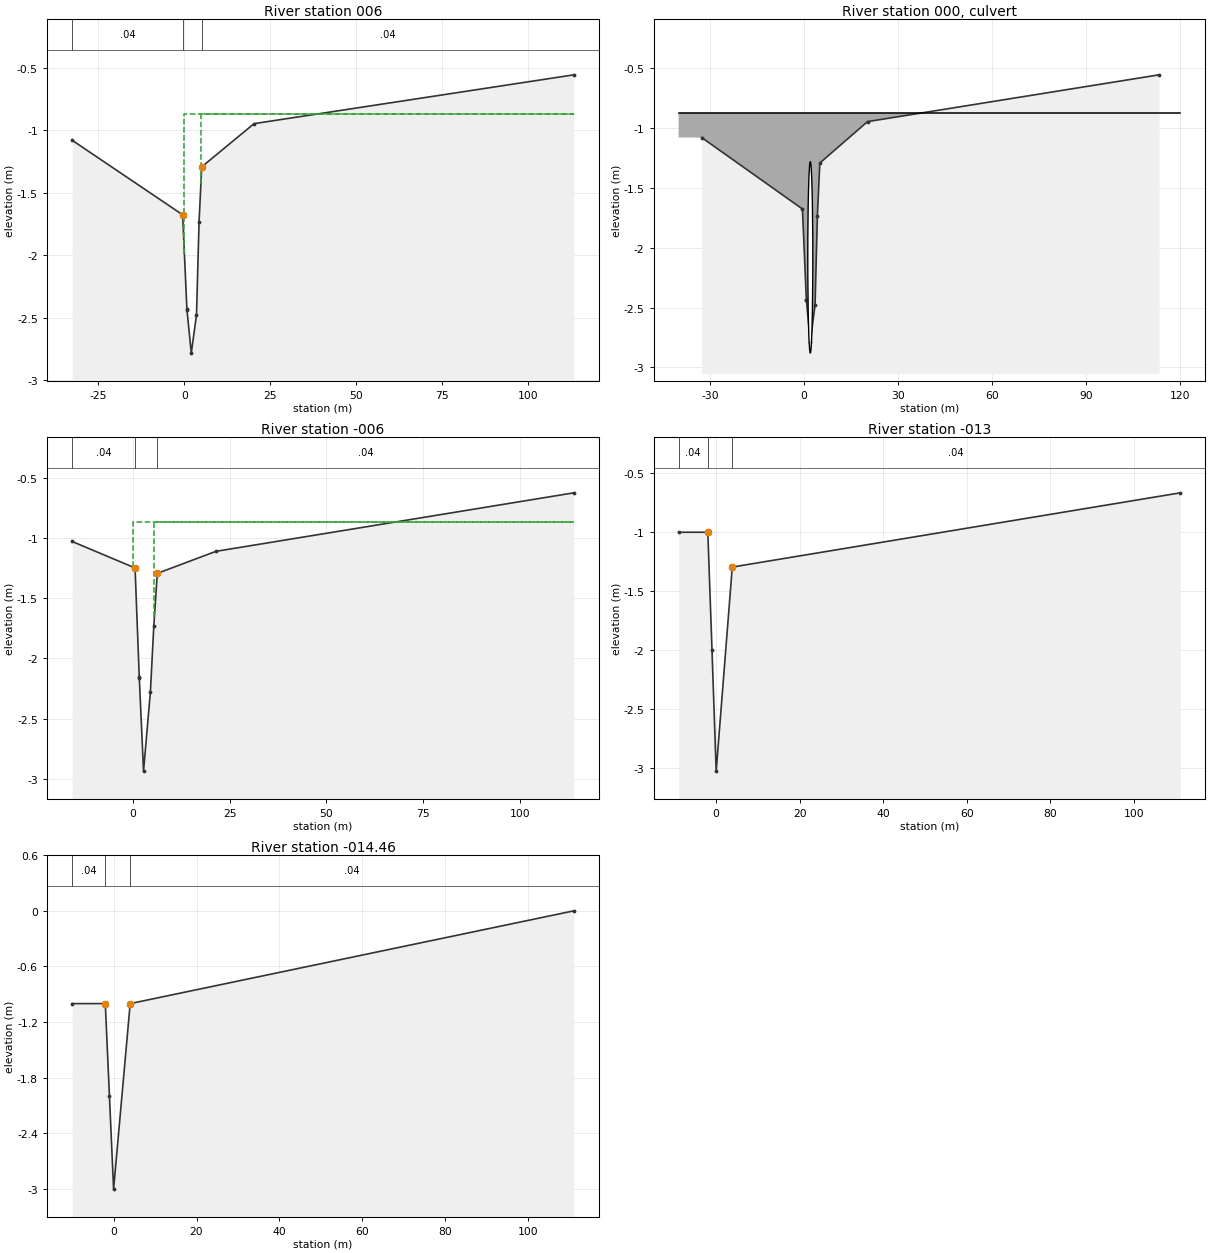
Type RM Length L Ch R = 1 ,006     ,12,12,12
XS GIS Cut Line= 6
412540.3294144694689642.43205039412528.5888026924689645.69858494
412507.3660650654689651.51450683412505.1023984494689651.99067776
412502.838731833 4689652.4668487412412.3897179764689677.26875188
#Sta/Elev= 10
 -32.635  -1.079    -.51  -1.676    .734  -2.434    .746  -2.437   2.001  -2.784
   3.517  -2.479   4.267  -1.731   5.039  -1.292  20.254   -.946 113.218   -.555
#Mann= 3 , 0 , 0
 -32.635     .04       0    -.51    .055       0   5.039     .04       0
#XS Ineff= 2 , 0
       0     -.8    -.87     4.8       0    -.87
Permanent Ineff=
       F       F
Bank Sta=-0.51,5.039
XS Rating Curve= 0 ,0
Exp/Cntr=0.8,0.6

Type RM Length L Ch R = 2 ,000     ,,,
BEGIN DESCRIPTION:
ODT Aguas abajo
END DESCRIPTION:
Bridge Culvert--1,0,-1,-1, 0
Deck Dist Width WeirC Skew NumUp NumDn MinLoCord MaxHiCord MaxSubmerge Is_Ogee
1.95,8.05,2.6,0, 2, 2, -0.87, , 0.98, 0, 0,0,,
     -40     120
    -.87    -.87
                
     -40     120
    -.87    -.87
                
BR Coef=-1 , 0 , 0 ,, 0 ,,,0.8,-1,,0,
WSPro=,,,, 1 ,,,, 0 ,,,, 0 ,,,,-1 ,-1 ,-1 , 0 , 0 , 0 , 0 , 0
Culvert=1,1.6,,8.05,0.014,0.5,1,1,1,-2.88,2,-2.95,2.74,Culvert #1  , 0 ,1.95
Culvert Bottom n=0.014
BC Design=,, 0 ,, 0 ,,,,,,
BC Use User HTab Curves=0
BC User HTab FreeFlow(D)= 0

Type RM Length L Ch R = 1 ,-006    ,3.5,3.5,3.5
XS GIS Cut Line= 6
412517.4476692554689635.02481044 412511.574754724689636.85590217
412510.2952542244689637.25183034 412497.455670344689641.03376544
412494.4619178554689641.80885946 412432.343434384689660.11179134
#Sta/Elev= 10
 -15.708  -1.029    .549  -1.249   1.633  -2.154   1.643  -2.161   2.737  -2.936
   4.511  -2.278   5.388  -1.733   6.291  -1.294  21.427  -1.111 113.905   -.625
#Mann= 3 , 0 , 0
 -15.708     .04       0    .549    .055       0   6.291     .04       0
#XS Ineff= 2 , 0
       0    -.06    -.87    5.54       0    -.87
Permanent Ineff=
       F       F
Bank Sta=0.549,6.291
XS Rating Curve= 0 ,0
Exp/Cntr=0.8,0.6

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
Type RM Length L Ch R = 1 ,-013    ,1.46,1.46,1.46
XS GIS Cut Line= 5
 412507.123118484689629.76135005412503.6530382874689630.98899688
412502.2018011734689631.50241632412500.7505640594689632.01583576
412447.0206586394689649.20856204
#Sta/Elev= 6
      -9      -1      -2      -1      -1      -2       0  -3.024   3.855  -1.295
 111.139   -.666
#Mann= 3 , 0 , 0
      -9     .04       0      -2    .055       0   3.855     .04       0
Bank Sta=-2,3.855
XS Rating Curve= 0 ,0
Exp/Cntr=0.8,0.6

Type RM Length L Ch R = 1 ,-014.46 ,0,0,0
XS GIS Cut Line= 5
412507.1676551484689628.19692039412503.2019837084689629.59989775
412501.7148569184689630.12601426412500.2277301274689630.65213078
412446.6746690834689647.90091509
#Sta/Elev= 6
     -10      -1      -2      -1      -1      -2       0      -3       4      -1
     111       0
#Mann= 3 , 0 , 0
     -10     .04       0      -2    .055       0       4     .04       0
Bank Sta=-2,4
XS Rating Curve= 0 ,0
Exp/Cntr=0.3,0.1

Chan Stop Cuts=-1
Use User Specified Reach Order=0
Composite Channel Slope=5